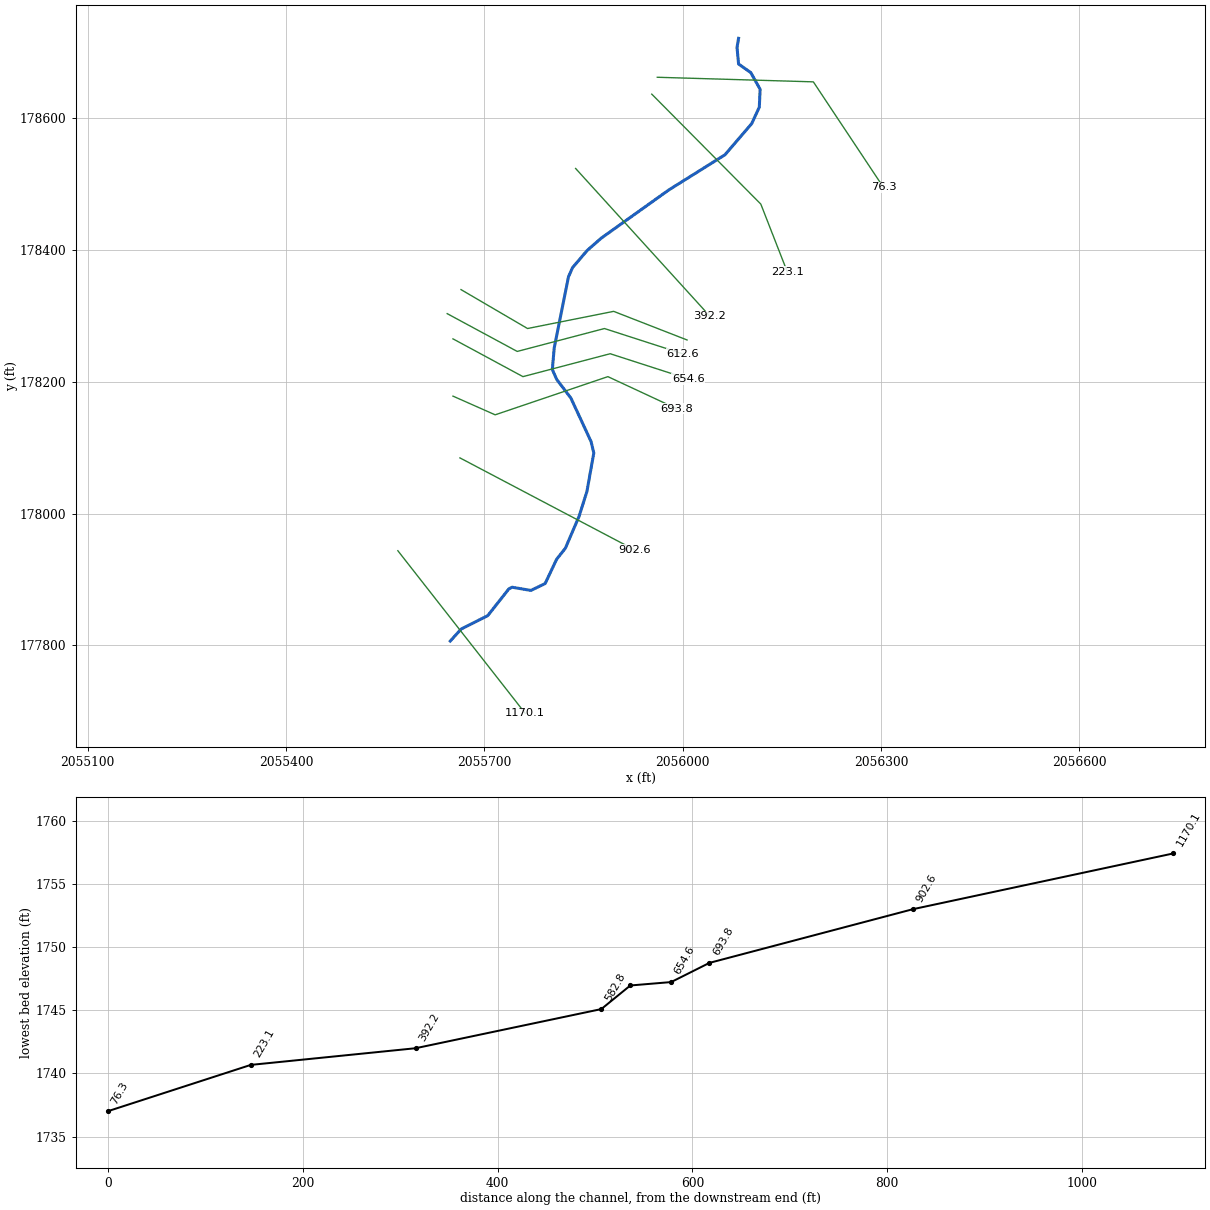
--- BLKLCKT1.prj (project) ---

Proj Title=BLKLCKT1
Current Plan=p01
Default Exp/Contr=0,0
English Units
Geom File=g01
Flow File=f01
Plan File=p01
BEGIN DESCRIPTION:
END DESCRIPTION:
DSS Export Rating Curves= 0
DSS Export Rating Curve Sorted= 0
DSS Export Volume Flow Curves= 0
DXF OffsetX= 0
DXF OffsetY= 0
DXF ScaleX= 0
DXF ScaleY= 0

--- BLKLCKT1.p01 (plan) ---

Plan Title=Floodplain
Program Version=4.00
Geom File=g01
Flow File=f01
K Sum by GR=0
Std Step Tol=0.01
Critical Tol=0.01
Num of Std Step Trials=20
Max Error Tol=0.3
Flow Tol Ratio=0.001
Split Flow NTrial=30
Split Flow Tol=0.02
Split Flow Ratio=0.02
Log Output Level=0
Friction Slope Method=1
Unsteady Friction Slope Method=2
Unsteady Bridges Friction Slope Method=1
Global Log Level=0
CheckData=False
Run HTab=0
Run UNet=0
Run PostProcess=0
UNET Theta=0
UNET Theta Warmup=0
UNET ZTol=0
UNET ZSATol=0
UNET MxIter=0
UNET MaxInSteps=0
UNET DtIC=0
UNET DtMin=0
UNET MaxCRTS=0
UNET WFStab=0
UNET SFStab=0
UNET WFX=0
UNET SFX=0
UNET DSS MLevel=0
UNET DZMax Abort=0
UNET Convert EG Bridges=0
UNET Use Existing IB Tables=0
UNET Froude Limit=0
UNET Froude Power=0
Write IC File=0
Echo Input=False
Echo Output=False
Write Detailed=0

--- BLKLCKT1.f01 (steady flow) ---

Flow Title=2010 USGS WV Regression Equation
Program Version=5.03
Number of Profiles= 1
Profile Names=P100yr
River Rch & RM=BLKLCKT1,Main            ,1170.1
510.4425
River Rch & RM=BLKLCKT1,Main            ,582.8
551.7904
River Rch & RM=BLKLCKT1,Main            ,223.1
555.1459
Boundary for River Rch & Prof#=BLKLCKT1,Main            , 1
Up Type= 0
Dn Type= 3
Dn Slope=0.02444
DSS Import GetInterval= 0
DSS Import GetPeak= 0
DSS Import FillOption= 0

--- BLKLCKT1.g01 (geometry) ---

Geom Title=LiDAR
Program Version=5.03

River Reach=BLKLCKT1        ,Main
Reach XY= 30
     2055648.577      177806.688      2055665.07      177824.917
     2055705.278      177845.241     2055737.118      177885.681
     2055742.084      177888.297     2055770.556      177883.436
     2055792.084      177893.852     2055809.445      177930.658
     2055822.639      177947.325     2055843.472      177995.935
     2055855.278      178033.436     2055865.695      178091.769
     2055861.528       178109.13     2055830.972      178175.102
     2055809.609      178203.208     2055802.988      178218.177
     2055805.766      178250.816     2055827.396      178358.771
     2055833.472       178372.66     2055855.608      178398.702
     2055876.875      178417.365     2055978.872      178490.282
     2056064.088      178543.777     2056104.584      178591.074
     2056116.034      178616.013     2056117.294      178643.003
     2056103.189      178668.322     2056084.688      178681.361
     2056082.332       178706.48     2056084.676      178720.285

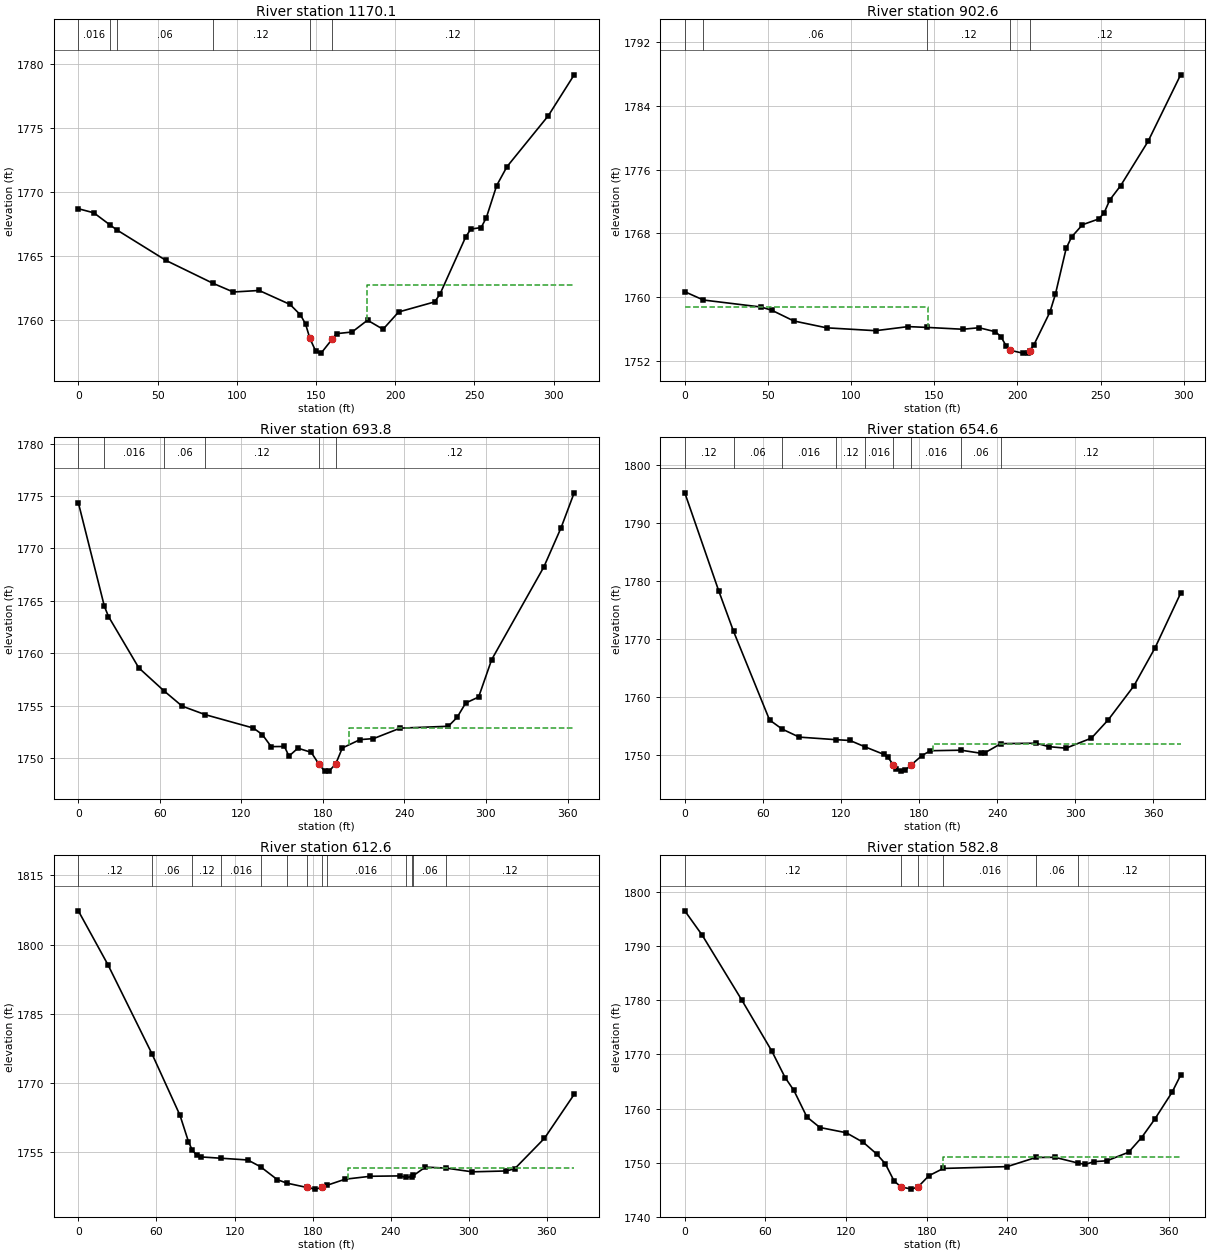
Type RM Length L Ch R = 1 ,1170.1  ,257.4,267.5,274.7
XS GIS Cut Line= 2
     2055569.296       177943.61     2055762.004      177697.083
#Sta/Elev= 30
       0  1768.7     9.8 1768.38   19.871767.445   24.491767.032    55.4 1764.66
   84.871762.885    97.8  1762.2   114.1 1762.32   133.6 1761.23   140.2 1760.41
   143.4  1759.7  146.131758.576   149.9 1757.56   153.2 1757.43   160.2 1758.52
     163 1758.95   172.8 1759.08   182.5    1760   192.3 1759.29   202.1 1760.64
   224.9 1761.43   228.2 1762.03   244.5 1766.51   247.7 1767.11   254.2 1767.23
   257.5 1768.01     264 1770.51   270.5 1771.98   296.6 1775.96   312.9 1779.15
#Mann= 6 ,-1 , 0
       0    .016       0   19.87     .08       0   24.49     .06       0
   84.87     .12       0  146.13    .045       0   160.2     .12       0
#XS Ineff= 2 , 0
                           182.4         1762.77
Permanent Ineff=
       F       F
Bank Sta=146.13,160.2
XS Rating Curve= 0 ,0
Exp/Cntr=0.3,0.1

Type RM Length L Ch R = 1 ,902.6   ,190.3,208.7,226.7
XS GIS Cut Line= 2
     2055663.162      178084.352     2055926.819       177945.23
#Sta/Elev= 30
       0  1760.7   11.19 1759.66    45.9 1758.78    52.4 1758.37    65.5 1757.04
    85.2 1756.18   114.7 1755.82   134.3 1756.33  145.75 1756.23   167.1    1756
   176.9 1756.19   186.7 1755.69     190 1755.09   193.3 1753.88  195.62 1753.37
   203.1 1753.01   206.4 1753.08  207.26 1753.32   209.7 1753.97   219.5 1758.14
   222.8 1760.37   229.3 1766.14   232.6 1767.57   239.1 1769.09     249 1769.82
   252.2 1770.62   255.5 1772.19   262.1    1774   278.5 1779.52   298.1 1787.86
#Mann= 5 ,-1 , 0
       0    .016       0   11.19     .06       0  145.75     .12       0
  195.62    .045       0  207.26     .12       0
#XS Ineff= 2 , 0
          146.44 1758.78
Permanent Ineff=
       F       F
Bank Sta=195.62,207.26
XS Rating Curve= 0 ,0
Exp/Cntr=0.3,0.1

Type RM Length L Ch R = 1 ,693.8   ,40.7,39.3,38.2
XS GIS Cut Line= 4
     2055652.629      178177.985     2055716.478      178149.614
     2055887.004      178207.499     2055991.171      178158.888
#Sta/Elev= 30
       0 1774.37   19.161764.489    22.2 1763.51    44.5 1758.61   62.961756.426
    76.4 1754.96   93.461754.144   128.8 1752.87   135.4 1752.25   141.9  1751.1
   151.7 1751.11     155 1750.19   161.6 1750.95   171.4 1750.55  176.791749.476
   181.2 1748.77   184.5 1748.76   189.4 1749.44   194.3 1750.97   207.4 1751.77
   217.2 1751.86   236.8 1752.86   272.3 1753.04   278.7 1753.88   285.1 1755.26
   294.6 1755.83   304.2  1759.4   342.6 1768.24   355.3 1771.99   364.9 1775.31
#Mann= 6 ,-1 , 0
       0     .06       0   19.16    .016       0   62.96     .06       0
   93.46     .12       0  176.79    .045       0   189.4     .12       0
#XS Ineff= 2 , 0
                          199.38         1752.86
Permanent Ineff=
       F       F
Bank Sta=176.79,189.4
XS Rating Curve= 0 ,0
Exp/Cntr=0.3,0.1

Type RM Length L Ch R = 1 ,654.6   ,42.1,41.9,42.2
XS GIS Cut Line= 4
     2055652.629      178264.791     2055758.532      178207.499
     2055890.477      178242.221     2056008.532      178204.027
#Sta/Elev= 30
       0 1795.27      26 1778.39   37.431771.372    65.1 1756.07   74.741754.501
    87.9 1753.11  116.251752.666   126.9 1752.53  138.811751.398   152.9 1750.13
   156.1 1749.62  160.321748.284   162.6  1747.6   165.9 1747.24   169.1 1747.36
   173.51748.228   182.1 1749.91   188.6 1750.76  212.271750.852   227.6 1750.32
   230.9 1750.45  242.811751.983   269.9 1752.06   279.7 1751.46   292.8  1751.2
   312.4 1752.94   325.4 1756.12     345 1761.95   361.3 1768.54   380.9 1777.94
#Mann= 9 ,-1 , 0
       0     .12       0   37.43     .06       0   74.74    .016       0
  116.25     .12       0  138.81    .016       0  160.32    .045       0
   173.5    .016       0  212.27     .06       0  242.81     .12       0
#XS Ineff= 2 , 0
                           190.3         1751.96
Permanent Ineff=
       F       F
Bank Sta=160.32,173.5
XS Rating Curve= 0 ,0
Exp/Cntr=0.3,0.1

Type RM Length L Ch R = 1 ,612.6   ,30.5,29.8,28.1
XS GIS Cut Line= 4
     2055643.949      178302.985     2055749.852      178245.694
     2055881.796      178280.416     2055999.852      178242.221
#Sta/Elev= 30
       0 1807.33    22.8 1795.61   56.521776.346    78.1 1762.98    84.6 1757.27
   87.621755.348    91.1 1754.34    94.4 1753.95  109.941753.664   130.2 1753.29
  139.99 1751.82   152.9 1749.02  160.151748.274   175.6 1747.33   182.1 1746.97
  187.361747.341   190.7 1747.77   204.9 1749.12   224.4 1749.76   247.1 1749.84
  251.781749.511  256.081749.667  257.471749.927   266.6 1751.75  282.751751.523
   302.6 1750.72   328.7 1750.91   335.2 1751.38   358.1    1758   380.9 1767.52
#Mann= 13 ,-1 , 0
       0     .12       0   56.52     .06       0   87.62     .12       0
  109.94    .016       0  139.99     .12       0  160.15     .06       0
   175.6    .045       0  187.36     .06       0   190.7    .016       0
  251.78     .06       0  256.08    .016       0  257.47     .06       0
  282.75     .12       0
#XS Ineff= 2 , 0
                          207.22         1751.59
Permanent Ineff=
       F       F
Bank Sta=175.6,187.36
XS Rating Curve= 0 ,0
Exp/Cntr=0.3,0.1

Type RM Length L Ch R = 1 ,582.8   ,214.2,190.6,166.3
XS GIS Cut Line= 4
     2055664.782      178339.444     2055765.477      178280.416
     2055895.685      178306.458     2056006.796      178263.055
#Sta/Elev= 30
       0 1796.54      13 1792.02    42.2 1780.13    64.8 1770.58    74.6 1765.73
    81.1 1763.36    90.8 1758.44   100.5 1756.49     120 1755.53   132.9 1753.72
   142.6 1751.62   149.1 1749.81   155.6 1746.64  160.631745.529   168.5  1745.1
   173.4 1745.48   181.5 1747.57  192.281748.924   239.8 1749.26  261.051750.949
   275.3 1750.98  292.771749.902   297.9 1749.67   304.3 1750.18     314 1750.34
   330.1 1751.92   339.8 1754.64   349.4 1757.97   362.4 1762.99   368.8 1766.16
#Mann= 6 ,-1 , 0
       0     .12       0  160.63    .045       0   173.4     .06       0
  192.28    .016       0  261.05     .06       0  292.77     .12       0
#XS Ineff= 2 , 0
                          191.95         1750.95
Permanent Ineff=
       F       F
Bank Sta=160.63,173.4
XS Rating Curve= 0 ,0
Exp/Cntr=0.3,0.1

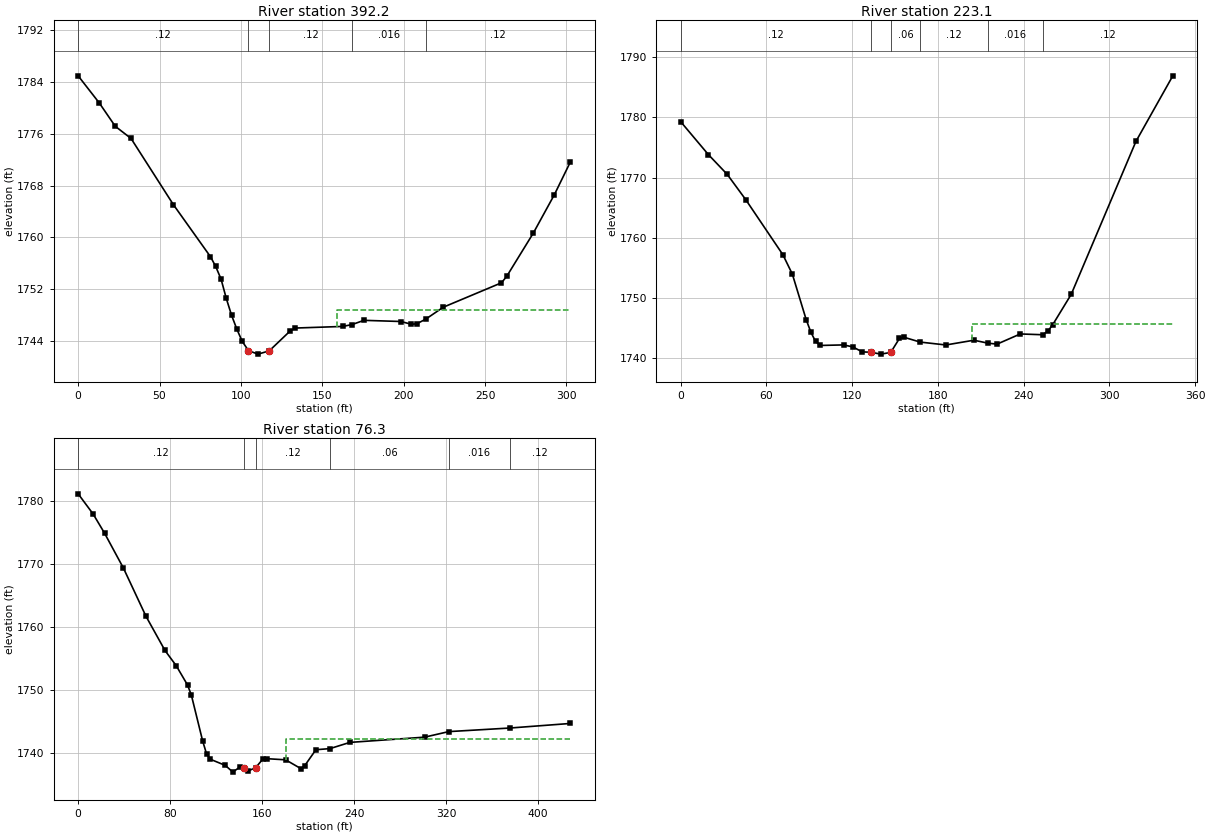
Type RM Length L Ch R = 1 ,392.2   ,167.7,169.1,169.8
XS GIS Cut Line= 2
     2055838.176      178523.037     2056041.301      178299.079
#Sta/Elev= 30
       0 1784.91      13 1780.72    22.8 1777.13    32.5 1775.25    58.5 1765.05
    81.3 1757.02    84.5 1755.52    87.8 1753.57      91  1750.6    94.3 1747.96
    97.5 1745.85   100.8 1743.97  104.651742.536   110.5    1742   117.4  1742.5
     130 1745.51   133.3 1746.02   162.6 1746.27  168.291746.559   175.6 1747.21
   198.3 1747.03   204.8  1746.6   208.1 1746.68  213.631747.407   224.3 1749.23
   260.1    1753   263.3 1753.99   279.6 1760.64   292.6 1766.59   302.4 1771.62
#Mann= 5 ,-1 , 0
       0     .12       0  104.65    .045       0   117.4     .12       0
  168.29    .016       0  213.63     .12       0
#XS Ineff= 2 , 0
                          158.93         1748.87
Permanent Ineff=
       F       F
Bank Sta=104.65,117.4
XS Rating Curve= 0 ,0
Exp/Cntr=0.3,0.1

Type RM Length L Ch R = 1 ,223.1   ,134.2,146.8,163.8
XS GIS Cut Line= 3
     2055953.411      178635.668     2056118.341      178469.001
     2056158.272       178366.57
#Sta/Elev= 30
       0 1779.29    19.5 1773.79    32.6 1770.53    45.6 1766.32    71.6 1757.17
    78.2 1753.95    87.9 1746.38    91.2 1744.29    94.4  1742.8    97.7 1742.12
     114 1742.21   120.5 1741.88     127 1741.06   133.5 1740.98     140 1740.68
  147.011740.958   153.1 1743.28   156.3 1743.48  167.591742.682   185.6  1742.2
   205.2 1742.99  215.051742.501   221.4 1742.34   237.7 1744.03  253.351743.898
   257.1 1744.54   260.4 1745.58   273.3  1750.6   318.6    1776   344.4 1786.89
#Mann= 6 ,-1 , 0
       0     .12       0   133.5    .045       0  147.01     .06       0
  167.59     .12       0  215.05    .016       0  253.35     .12       0
#XS Ineff= 2 , 0
                          204.08         1745.66
Permanent Ineff=
       F       F
Bank Sta=133.5,147.01
XS Rating Curve= 0 ,0
Exp/Cntr=0.3,0.1

Type RM Length L Ch R = 1 ,76.3    ,77.6,76.3,68.5
XS GIS Cut Line= 3
     2055961.657      178661.275     2056197.768      178654.331
     2056303.671      178494.609
#Sta/Elev= 30
       0  1781.1    13.1 1777.88      23 1774.85    39.4 1769.32      59 1761.69
    75.5 1756.28    85.3 1753.86    95.1 1750.81    98.4 1749.23   108.3  1741.9
   111.6 1739.93   114.8 1739.06     128 1738.07   134.5 1737.01   141.1 1737.89
   144.4 1737.66   147.6  1737.2   154.2 1737.69   160.8 1739.13     164 1739.14
   180.4 1738.96   193.6 1737.57   196.8 1737.99   206.7 1740.56  218.911740.735
   236.2 1741.72   301.2 1742.55  322.191743.429  375.58    1744   427.9 1744.72
#Mann= 6 ,-1 , 0
       0     .12       0   144.4    .045       0   154.2     .12       0
  218.91     .06       0  322.19    .016       0  375.58     .12       0
#XS Ineff= 2 , 0
                          181.11         1742.26
Permanent Ineff=
       F       F
Bank Sta=144.4,154.2
XS Rating Curve= 0 ,0
Exp/Cntr=0.3,0.1
LCMann Table=0

Chan Stop Cuts=-1
Use User Specified Reach Order=0
Composite Channel Slope=5